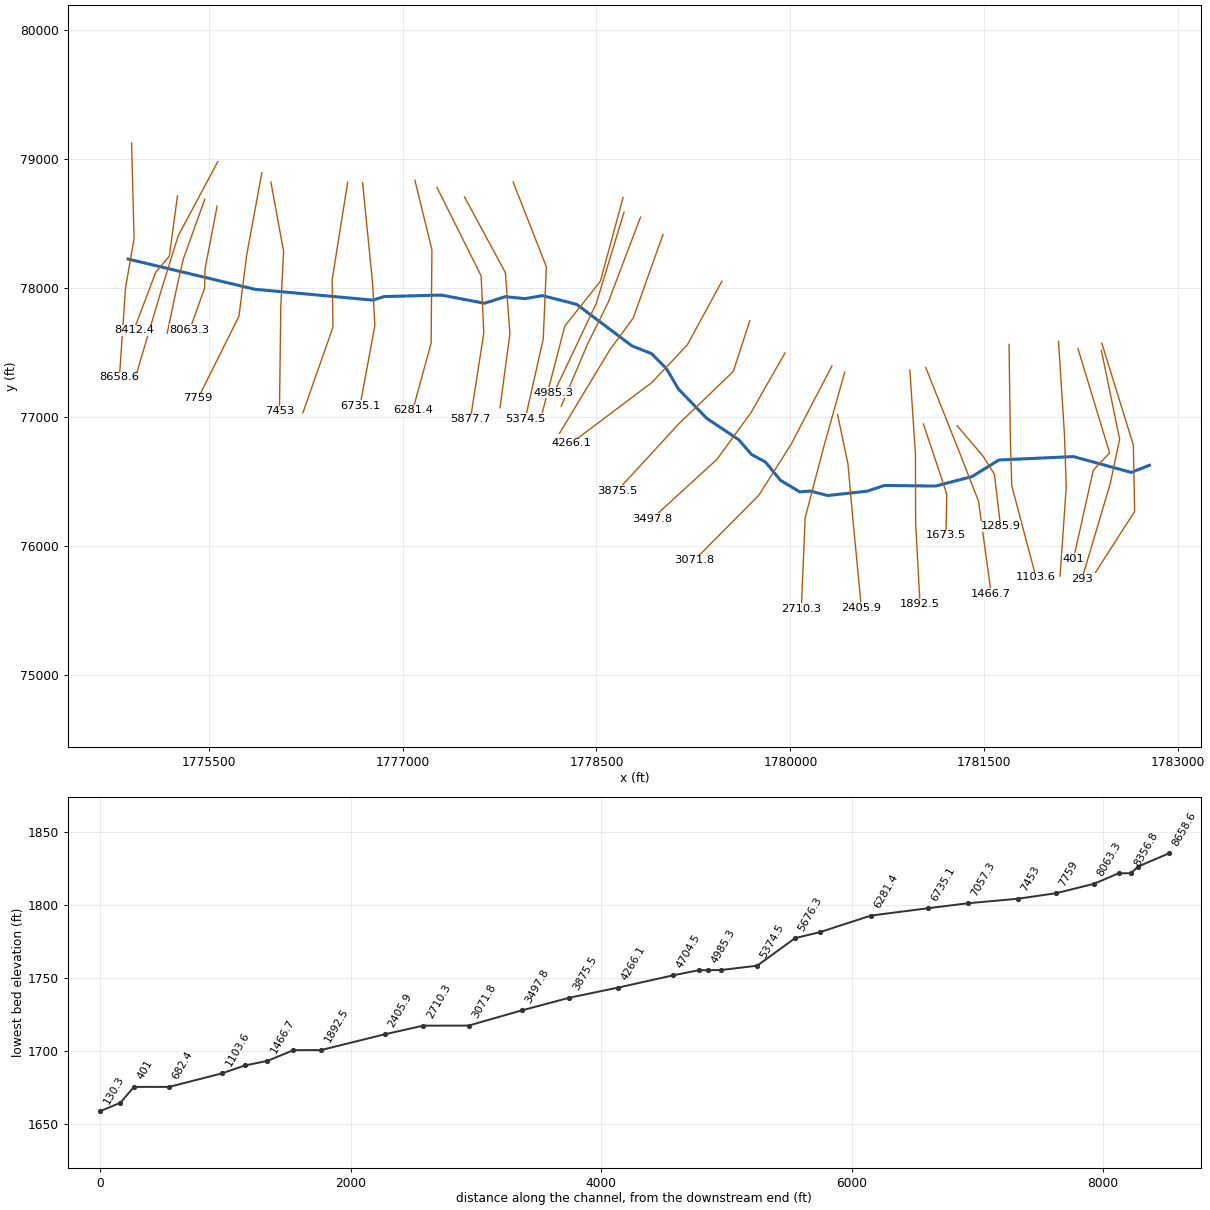
--- Beech Fork Trib 1.prj (project) ---

Proj Title=Beech Fork Trib 1
Current Plan=p01
Default Exp/Contr=0,0
English Units
Geom File=g01
Flow File=f01
Plan File=p01
BEGIN DESCRIPTION:
END DESCRIPTION:
DSS Export Rating Curves= 0
DSS Export Rating Curve Sorted= 0
DSS Export Volume Flow Curves= 0
DXF OffsetX= 0
DXF OffsetY= 0
DXF ScaleX= 0
DXF ScaleY= 0

--- Beech Fork Trib 1.p01 (plan) ---

Plan Title=Floodplain
Program Version=4.00
Geom File=g01
Flow File=f01
K Sum by GR=0
Std Step Tol=0.01
Critical Tol=0.01
Num of Std Step Trials=20
Max Error Tol=0.3
Flow Tol Ratio=0.001
Split Flow NTrial=30
Split Flow Tol=0.02
Split Flow Ratio=0.02
Log Output Level=0
Friction Slope Method=1
Unsteady Friction Slope Method=2
Unsteady Bridges Friction Slope Method=1
Global Log Level=0
CheckData=False
Run HTab=0
Run UNet=0
Run PostProcess=0
UNET Theta=0
UNET Theta Warmup=0
UNET ZTol=0
UNET ZSATol=0
UNET MxIter=0
UNET MaxInSteps=0
UNET DtIC=0
UNET DtMin=0
UNET MaxCRTS=0
UNET WFStab=0
UNET SFStab=0
UNET WFX=0
UNET SFX=0
UNET DSS MLevel=0
UNET DZMax Abort=0
UNET Convert EG Bridges=0
UNET Use Existing IB Tables=0
UNET Froude Limit=0
UNET Froude Power=0
Write IC File=0
Echo Input=False
Echo Output=False
Write Detailed=0

--- Beech Fork Trib 1.f01 (steady flow) ---

Flow Title=NFF Regression Equation
Program Version=4.00
Number of Profiles=1
Profile Names=P100yr
River Rch & RM=Beech Fork Tr...,Main      ,8658.6
542.2259
River Rch & RM=Beech Fork Tr...,Main      ,8658.6
820.7491
River Rch & RM=Beech Fork Tr...,Main      ,8356.8
744.8246
River Rch & RM=Beech Fork Tr...,Main      ,5676.3
904.4339
River Rch & RM=Beech Fork Tr...,Main      ,5374.5
979.1599
River Rch & RM=Beech Fork Tr...,Main      ,2710.3
1048.265
River Rch & RM=Beech Fork Tr...,Main      ,2405.9
1182.968
River Rch & RM=Beech Fork Tr...,Main      ,293
1257.652
Boundary for River Rch & Prof#=Beech Fork Tr...,Main      ,1
Up Type=0
Dn Type=3
Dn Slope=0.057882

--- Beech Fork Trib 1.g01 (geometry) ---

Geom Title=USGS 10m DEM
Program Version=4.00

River Reach=Beech Fork Tr...,Main
Reach XY= 30
     1774876.884       78224.929     1775856.353       77990.477
     1776770.082        77906.08     1776857.906       77933.814
     1777300.413       77945.373     1777633.626       77881.735
     1777793.991       77933.088     1777948.121       77917.553
     1778081.722       77941.109     1778346.934       77873.241
     1778775.366       77550.292     1778926.753       77490.572
     1779039.942       77375.655     1779134.591       77215.559
     1779354.435        76987.28     1779600.077       76823.325
     1779699.233       76708.435      1779807.63       76649.078
     1779924.298       76506.847     1780073.774       76417.615
     1780153.966       76424.453      1780288.36       76389.471
     1780595.119       76423.316     1780726.676       76467.613
     1781123.755       76463.072     1781405.264       76536.672
      1781613.85       76665.428     1782189.313       76691.804
     1782637.136       76568.906     1782777.399       76624.254

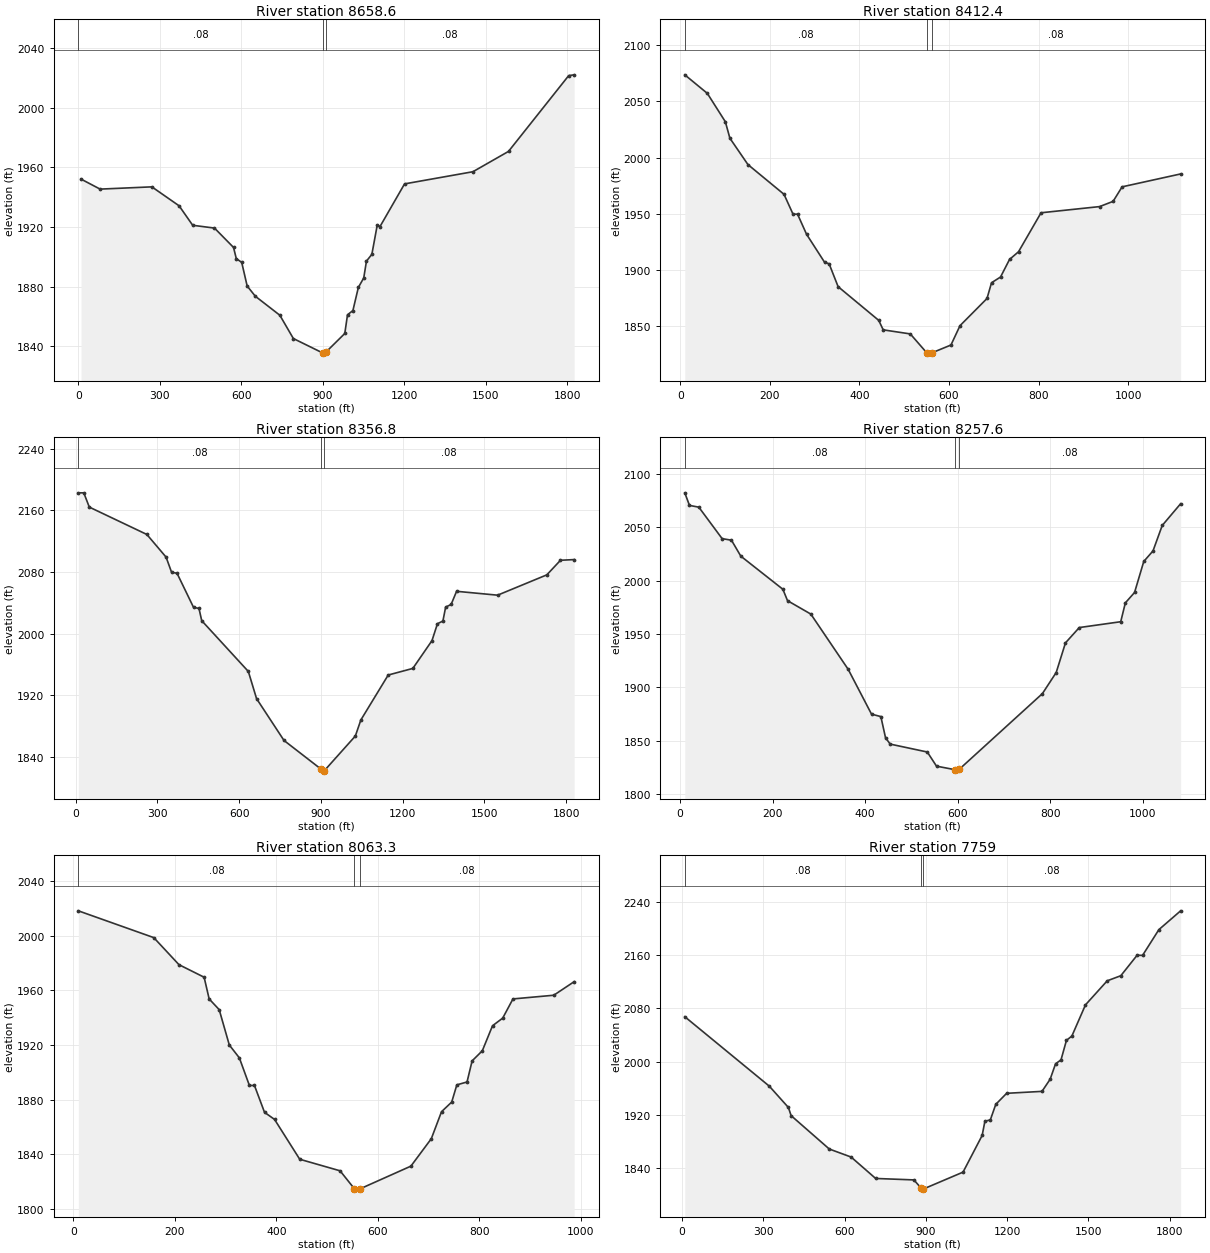
Type RM Length L Ch R = 1 ,8658.6  ,257.1,246.2,235.4
XS GIS Cut Line= 4
     1774903.629       79125.434     1774922.747       78383.568
     1774856.586       78000.532     1774809.372       77306.911
#Sta/Elev= 30
      10 1952.19    80.2 1945.47   270.8 1946.99   371.1 1934.26   421.2 1921.18
   501.4 1919.31   571.6 1906.29   581.7 1898.83   601.7 1896.26   621.8 1880.38
   651.9 1873.52   742.1 1860.77   791.9 1845.13   901.1 1835.35   901.6 1835.33
   911.1 1835.89   981.3 1848.52   991.3 1861.08  1011.2 1863.92  1031.2 1879.43
  1051.1 1885.82  1061.1 1897.12    1081 1901.67  1100.9  1921.4  1110.9 1920.31
  1201.4 1948.98  1453.2 1957.15  1584.2 1970.79  1805.9  2021.7    1826 2022.22
#Mann= 3 , 0 , 0
       0     .08       0   901.1    .045       0   911.1     .08       0
Bank Sta=901.1,911.1
XS Rating Curve= 0 ,0
Exp/Cntr=0.3,0.1

Type RM Length L Ch R = 1 ,8412.4  ,47.4,55.6,63.7
XS GIS Cut Line= 4
     1775258.426       78716.336     1775195.703       78247.122
     1775091.178       78124.183     1774920.863       77672.608
#Sta/Elev= 30
    10.1 2073.43    60.4 2056.97   100.7 2031.73   110.8 2017.13   151.1 1993.73
   231.7  1967.3   251.8 1949.68   261.9 1949.68     282 1931.83   322.3 1906.93
   332.4  1905.6   352.5 1885.29   443.2 1855.36   453.2 1846.93   513.7 1843.32
  549.92 1826.79   554.1 1826.26   561.2 1826.41   604.5 1833.46   624.7 1850.65
     685 1874.79   695.1 1888.77   715.2 1893.85   735.3 1909.46   755.4  1916.3
   805.7 1950.92   936.4  1956.4   966.6 1961.05   986.7 1973.95  1117.4  1985.4
#Mann= 3 , 0 , 0
    10.1     .08       0  549.92    .045       0   561.2     .08       0
Bank Sta=549.92,561.2
XS Rating Curve= 0 ,0
Exp/Cntr=0.3,0.1

Type RM Length L Ch R = 1 ,8356.8  ,97.6,99.2,100.7
XS GIS Cut Line= 4
     1775570.879        78982.05     1775263.997       78404.461
      1775138.64       78000.532      1774925.02       77278.993
#Sta/Elev= 30
    10.1 2182.61    30.2 2182.57    50.3 2164.12   261.6 2128.61   332.1 2099.22
   352.2 2079.65   372.3 2078.28   432.7  2034.2   452.8 2032.64   462.9 2016.83
   633.9 1950.99   664.1 1915.73   764.8  1861.5  901.91    1824   905.8 1821.73
   911.7 1821.86  1026.6 1867.25  1046.8 1888.07  1147.2 1946.36  1237.5 1954.91
  1307.8 1990.95  1327.8 2012.85  1347.9 2016.38  1357.9 2034.42    1378 2037.86
  1398.1 2054.91  1548.6 2049.89  1729.2 2076.24  1779.3 2095.15  1829.5 2096.04
#Mann= 3 , 0 , 0
    10.1     .08       0  901.91    .045       0   911.7     .08       0
Bank Sta=901.91,911.7
XS Rating Curve= 0 ,0
Exp/Cntr=0.3,0.1

Type RM Length L Ch R = 1 ,8257.6  ,190.3,194.3,198.4
XS GIS Cut Line= 4
     1775469.887       78689.176     1775303.046       78223.572
     1775256.486       78019.871     1775178.885       77649.327
#Sta/Elev= 30
    10.1 2082.24    20.2 2070.45    40.4 2068.83    90.8 2039.35     111 2037.89
   131.2 2022.96   222.1 1991.97   232.2 1981.28   282.6 1968.71   363.4 1916.97
   413.8 1875.05     434 1872.75   444.1 1852.91   454.2    1847   534.4 1839.59
   554.3 1826.36   593.3 1823.12   594.1  1821.7     604 1823.63   783.3 1894.28
   813.1 1914.03   833.1 1941.75     863 1956.11   952.6 1961.57   962.6 1979.23
   982.5 1988.95  1002.4 2017.98  1022.4 2027.87  1042.3 2051.67  1082.1 2072.03
#Mann= 3 , 0 , 0
    10.1     .08       0   593.3    .045       0     604     .08       0
Bank Sta=593.3,604
XS Rating Curve= 0 ,0
Exp/Cntr=0.3,0.1

Type RM Length L Ch R = 1 ,8063.3  ,306.3,304.4,302.3
XS GIS Cut Line= 4
     1775564.948       78634.856     1775471.827       78147.912
     1775467.947        77998.53     1775353.486       77676.488
#Sta/Elev= 30
     9.9 2018.27   158.6 1998.65   208.2 1978.85   257.8 1969.66   267.7 1953.77
   287.5 1945.92   307.4 1920.06   327.2 1910.62     347 1890.42     357  1890.4
   376.8 1870.75   396.6 1865.54   446.2 1836.39   525.7 1827.93     554 1814.75
  555.49 1814.52     564 1814.55   665.3 1831.36   705.5 1851.44   725.6 1871.19
   745.7 1878.27   755.8 1890.86   775.9 1892.96   785.9  1908.4     806  1915.8
   826.1 1934.12   846.2 1939.73   866.4 1953.77   946.8 1956.47     987  1966.4
#Mann= 3 , 0 , 0
     9.9     .08       0     554    .045       0     564     .08       0
Bank Sta=554,564
XS Rating Curve= 0 ,0
Exp/Cntr=0.3,0.1

Type RM Length L Ch R = 1 ,7759    ,304.5,306,307.5
XS GIS Cut Line= 4
     1775911.135       78894.803     1775793.283       78251.246
     1775734.086       77781.157     1775417.247       77142.988
#Sta/Elev= 30
    10.1 2067.52   322.1    1963   392.6 1930.91   402.6 1918.64   543.5  1868.4
   624.1 1856.32   714.7 1824.09   855.9  1821.9  882.18 1809.78   886.1 1808.03
  890.65 1808.18  1037.3 1833.61  1107.9 1888.83    1118 1910.17  1138.1 1912.26
  1158.2 1935.66  1198.3 1952.25  1328.8 1955.16  1358.9 1973.44  1378.9 1996.69
    1399 2002.57  1419.1    2032  1439.1 2038.43  1489.3 2085.36  1569.6 2121.59
  1619.8 2129.24    1680 2160.07  1700.1 2159.86  1760.3  2198.6  1840.6 2226.91
#Mann= 3 , 0 , 0
    10.1     .08       0  882.18    .045       0  890.65     .08       0
Bank Sta=882.18,890.65
XS Rating Curve= 0 ,0
Exp/Cntr=0.3,0.1

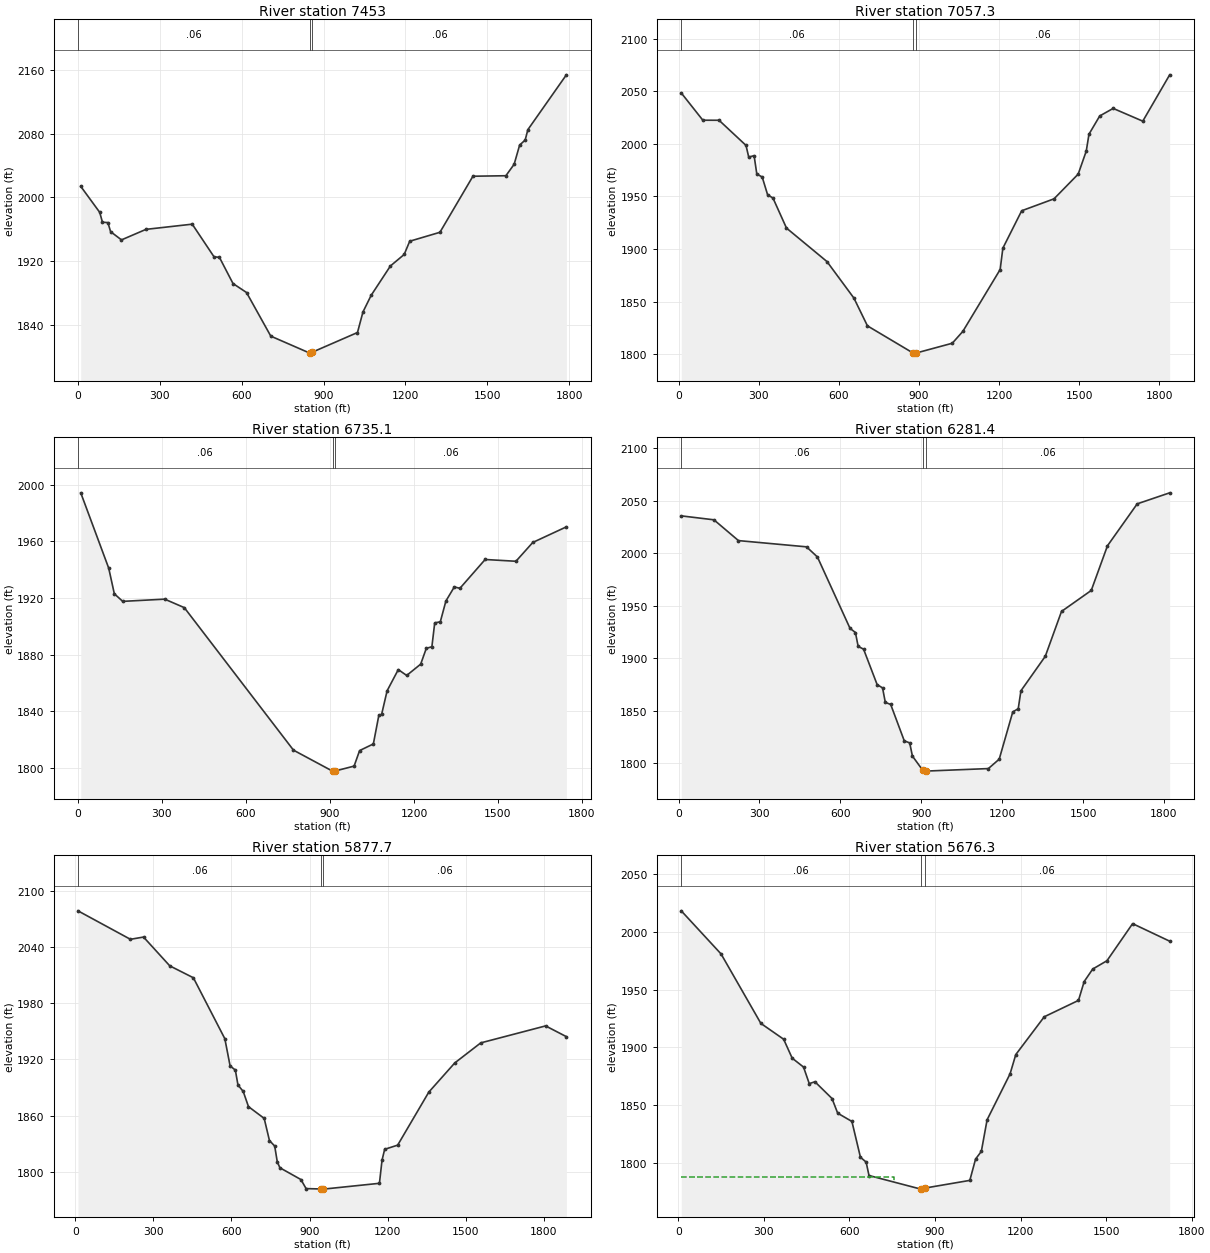
Type RM Length L Ch R = 1 ,7453    ,394.2,395.6,397
XS GIS Cut Line= 4
     1775981.319       78822.318     1776079.652       78282.843
     1776057.926       77857.764     1776047.299       77041.867
#Sta/Elev= 30
      10    2014    79.8 1981.21    89.7 1968.83   109.7 1968.35   119.6 1956.95
   159.5 1946.61   249.3 1959.84   418.8 1966.38   498.5 1925.41   518.5 1924.62
   568.2 1891.74   617.7 1880.46   706.7  1825.6   849.4 1804.28   855.2 1804.23
   859.4 1805.51  1024.4 1830.14  1044.5    1856  1074.7 1877.01  1145.2 1913.86
  1195.6 1928.29  1215.8 1944.92  1326.6 1956.16  1447.5 2026.65  1568.3 2027.28
  1598.6 2041.71  1618.7 2065.85  1638.9  2072.1  1648.9 2085.23    1790 2154.15
#Mann= 3 , 0 , 0
       0     .06       0   849.4    .045       0   859.4     .06       0
Bank Sta=849.4,859.4
XS Rating Curve= 0 ,0
Exp/Cntr=0.3,0.1

Type RM Length L Ch R = 1 ,7057.3  ,321.6,322.3,323
XS GIS Cut Line= 4
     1776575.436       78821.316     1776454.891       78063.211
     1776461.855       77697.585     1776228.965       77032.133
#Sta/Elev= 30
    10.1  2048.4    90.9 2022.46   151.5 2022.44   252.5 1998.53   262.6 1987.45
   282.8 1988.79   292.9 1971.35   313.1 1968.48   333.3 1951.66   353.5 1948.47
     404 1919.98   555.5 1888.17   656.5 1853.41     707 1827.07   878.3 1801.19
  886.14 1801.16   888.3  1801.2  1024.6 1810.56  1064.1 1821.83  1203.8 1880.62
  1213.9  1900.9  1284.4 1936.44  1405.3 1947.76  1495.9 1971.27  1526.1 1993.17
  1536.2 2009.18  1576.5 2026.53  1626.8  2033.7  1737.6 2021.57  1838.3  2065.6
#Mann= 3 , 0 , 0
    10.1     .06       0   878.3    .045       0   888.3     .06       0
Bank Sta=878.3,888.3
XS Rating Curve= 0 ,0
Exp/Cntr=0.3,0.1

Type RM Length L Ch R = 1 ,6735.1  ,454.8,453.6,452.5
XS GIS Cut Line= 4
     1776690.708       78817.599     1776768.284       78031.871
     1776785.694       77708.032     1776670.784        77088.21
#Sta/Elev= 30
      10 1994.24   109.9 1940.99   129.9 1922.93   159.9 1917.59   309.8 1919.16
   379.8 1913.16   769.6 1812.52     909 1797.72   917.3 1797.71     919 1797.83
   986.1 1801.26  1005.8 1812.22  1054.9 1816.91  1074.5 1837.15  1084.4 1837.78
    1104 1854.45  1143.9  1869.4  1173.9 1865.27  1223.9 1873.26  1243.9  1884.4
  1263.9 1885.55    1274 1902.38    1294 1903.17    1314 1917.87    1344 1927.79
    1364 1926.81  1454.1 1947.16  1564.1 1945.91  1624.2 1959.19  1744.2 1970.21
#Mann= 3 , 0 , 0
       0     .06       0     909    .045       0     919     .06       0
Bank Sta=909,919
XS Rating Curve= 0 ,0
Exp/Cntr=0.3,0.1

Type RM Length L Ch R = 1 ,6281.4  ,402.2,403.7,405.1
XS GIS Cut Line= 4
     1777095.605       78836.247     1777226.894       78296.606
     1777220.962       77572.228     1777078.195       77049.906
#Sta/Elev= 30
    10.1 2035.81   131.3 2032.04   222.2 2012.25   474.6 2006.31     515 1996.66
   635.9  1928.7     656 1924.69   666.1 1911.49   686.2 1908.85   736.5 1875.08
   756.6 1871.97   766.7 1858.21   786.8 1856.15   837.1 1821.54   857.2 1819.59
   867.3 1807.04  905.46 1793.58   907.5 1792.69   917.6 1792.73    1149 1795.12
  1189.2 1804.08  1239.5 1849.12  1259.7 1852.11  1269.7  1869.2    1360 1902.04
  1420.2 1944.79  1530.5 1964.78  1590.6  2007.3  1700.9 2047.25  1821.3 2057.75
#Mann= 3 , 0 , 0
    10.1     .06       0  905.46    .045       0   917.6     .06       0
Bank Sta=905.46,917.6
XS Rating Curve= 0 ,0
Exp/Cntr=0.3,0.1

Type RM Length L Ch R = 1 ,5877.7  ,201,201.5,202
XS GIS Cut Line= 4
      1777266.23       78780.532     1777607.481        78094.55
     1777628.373       77652.317     1777524.819        76981.96
#Sta/Elev= 30
    10.1 2078.47   211.7 2048.07   262.1 2050.48   362.9 2019.75   453.7 2007.01
   574.6 1941.95   594.8 1912.96     615 1908.46     625 1892.59   645.2 1885.68
   665.4 1869.47   725.8 1856.91     746 1833.29   766.2 1827.39   776.2 1810.43
   786.3 1804.19   866.8 1791.67   886.9 1781.97  943.57 1781.57  947.26 1781.41
  953.73 1781.42  1168.7 1787.62  1178.7 1812.25  1188.8 1823.91  1238.8 1828.37
  1358.5 1884.98  1458.3 1916.12    1558  1937.5  1807.4 1955.64  1887.2 1944.16
#Mann= 3 , 0 , 0
    10.1     .06       0  943.57    .045       0  953.73     .06       0
Bank Sta=943.57,953.73
XS Rating Curve= 0 ,0
Exp/Cntr=0.3,0.1

Type RM Length L Ch R = 1 ,5676.3  ,303.6,301.8,299.9
XS GIS Cut Line= 4
     1777478.641       78707.407     1777795.516       78118.925
     1777830.338       77645.353     1777753.731       77070.799
#Sta/Elev= 30
      10 2018.27   149.6 1980.92   289.3 1920.74   369.1 1907.05     399 1890.66
   438.9 1882.92   458.9  1868.6   478.8 1870.21   538.7 1855.71   558.6    1843
   608.5 1835.83   638.4 1804.82   658.4 1800.64   668.4    1789   850.2 1777.22
   860.3 1777.21  863.66 1778.09    1022 1784.78  1042.2 1803.27  1062.4 1809.89
  1082.6 1837.28  1163.2 1877.08  1183.2 1893.75  1283.1  1926.5  1403.1 1940.68
    1423 1956.99    1453 1967.84    1503 1975.05  1592.9 2007.17  1722.9 1991.97
#Mann= 3 , 0 , 0
      10     .06       0   850.2    .045       0  863.66     .06       0
#XS Ineff= 2 , 0
          757.08 1787.36
Permanent Ineff=
       F       F
Bank Sta=850.2,863.66
XS Rating Curve= 0 ,0
Exp/Cntr=0.3,0.1

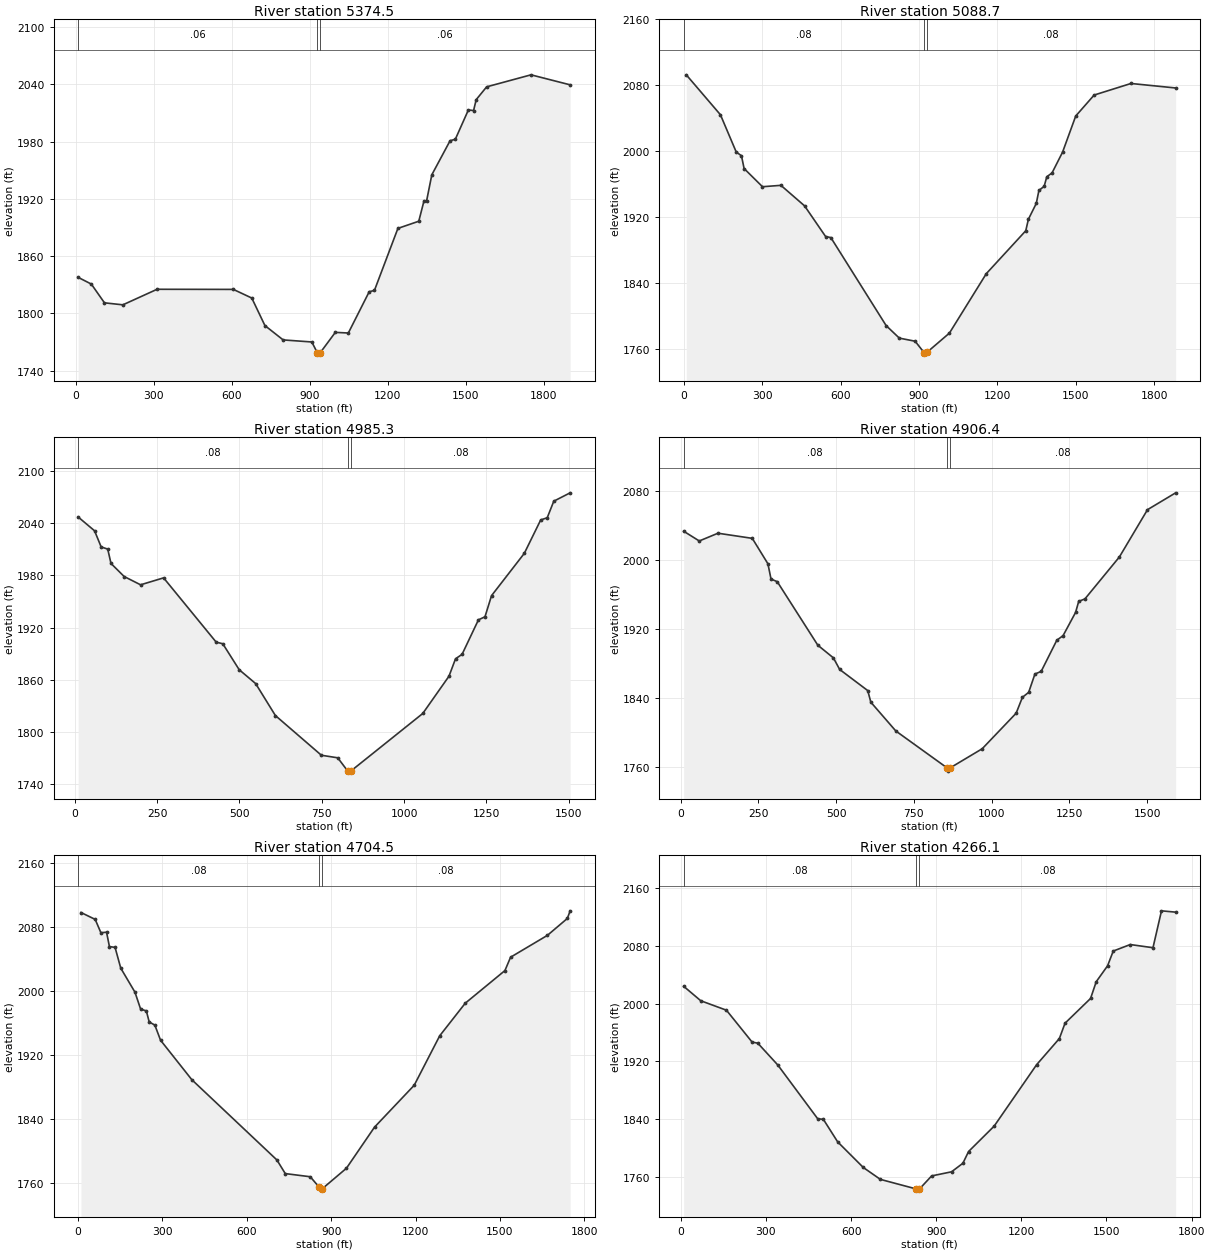
Type RM Length L Ch R = 1 ,5374.5  ,298.3,285.8,273.2
XS GIS Cut Line= 4
     1777855.056       78823.354     1778112.392       78164.193
     1778088.017       77603.567     1777949.695        76987.19
#Sta/Elev= 30
    10.1 1837.72    60.7 1830.69   111.2 1811.04     182 1808.94   313.4 1825.23
   606.5  1825.1   677.3 1816.05   727.7 1787.23   797.8 1772.18     908 1770.02
   929.7 1758.39  938.18 1758.34   939.7 1758.54   998.2 1780.08  1048.3 1779.42
  1128.5  1822.7  1148.5 1824.01  1238.7 1889.02  1318.9 1896.52    1339 1917.91
    1349 1917.91    1369 1945.16  1439.2 1980.87  1459.3 1982.38  1509.4 2013.05
  1529.5  2012.5  1539.5 2023.89  1579.6  2037.3  1750.1  2049.9  1900.5 2039.41
#Mann= 3 , 0 , 0
    10.1     .06       0   929.7    .045       0   939.7     .06       0
Bank Sta=929.7,939.7
XS Rating Curve= 0 ,0
Exp/Cntr=0.3,0.1

Type RM Length L Ch R = 1 ,5088.7  ,98.8,103.4,108
XS GIS Cut Line= 4
     1778705.744       78702.929     1778530.249       78052.764
      1778255.16        77704.55     1778063.467       76964.785
#Sta/Elev= 30
    10.1 2092.83   140.7  2044.4     201 1999.27   221.1 1994.67   231.2 1979.18
   301.5 1957.14   371.9 1958.83   462.4 1933.94   542.8 1896.77   562.9 1895.46
   774.3 1788.76   824.7 1773.57   885.2  1769.8   919.9 1755.79   925.6 1755.37
   929.9  1756.2  1016.3 1779.66  1157.4 1851.76  1308.2 1903.75  1318.3 1917.69
  1348.5 1936.96  1358.5 1952.64  1378.6 1957.66  1388.7 1969.24  1408.8 1973.93
    1449 1999.11  1499.3 2042.89  1569.7 2068.31  1710.5 2082.33  1881.4 2076.89
#Mann= 3 , 0 , 0
       0     .08       0   919.9    .045       0   929.9     .08       0
Bank Sta=919.9,929.9
XS Rating Curve= 0 ,0
Exp/Cntr=0.3,0.1

Type RM Length L Ch R = 1 ,4985.3  ,79.3,78.9,78.6
XS GIS Cut Line= 4
     1778712.866       78587.547     1778498.451       77880.354
     1778366.793        77601.99     1778171.186       77188.207
#Sta/Elev= 30
      10  2046.8    59.9 2030.94    79.9 2012.45    99.9 2009.94   109.8 1993.48
   149.8 1978.49   199.7 1968.98   269.6 1976.95   429.4 1903.18   449.4 1901.36
   499.3 1871.55   549.2 1855.68   609.2    1819   748.9 1773.45   798.6  1770.5
     829 1755.31  838.28 1755.23     839 1755.51  1056.9 1821.37  1136.5  1864.1
  1156.4 1884.11  1176.3 1889.21    1226 1928.79  1245.9 1932.32  1265.8 1956.53
  1365.3 2005.04  1415.1 2043.35    1435 2045.93  1454.9 2064.91  1504.6  2074.5
#Mann= 3 , 0 , 0
      10     .08       0     829    .045       0     839     .08       0
Bank Sta=829,839
XS Rating Curve= 0 ,0
Exp/Cntr=0.3,0.1

Type RM Length L Ch R = 1 ,4906.4  ,205.4,201.9,198.3
XS GIS Cut Line= 4
     1778840.763       78549.931     1778588.731       77884.115
     1778430.741       77564.373     1778227.611        77082.88
#Sta/Elev= 30
      10 2033.76    60.2 2022.43   120.3 2031.43   230.6 2025.47   280.8 1995.96
   290.8 1978.19   310.8 1975.18   441.2  1901.4   491.3 1886.68   511.4 1873.26
   601.6 1848.72   611.6 1835.24   691.9 1801.81   855.3  1759.3   860.5  1755.2
   865.3 1758.72   969.5 1781.19  1078.6 1822.47  1098.7 1840.89  1118.8 1846.68
  1138.9 1867.92    1159 1870.99  1209.3  1907.2  1229.4 1912.52  1269.6 1939.49
  1279.6 1952.26  1299.7  1955.2  1410.3 2003.83  1500.7 2058.76  1591.2 2078.33
#Mann= 3 , 0 , 0
      10     .08       0   855.3    .045       0   865.3     .08       0
Bank Sta=855.3,865.3
XS Rating Curve= 0 ,0
Exp/Cntr=0.3,0.1

Type RM Length L Ch R = 1 ,4704.5  ,440.9,438.4,435.9
XS GIS Cut Line= 4
     1779014.267       78414.907     1778784.446       77767.228
     1778603.374       77519.996     1778213.663       76871.856
#Sta/Elev= 30
    10.1 2098.01    60.6 2089.39    80.9 2072.75   101.1 2073.32   111.2 2055.44
   131.4 2054.28   151.6 2028.33   202.1 1998.28   222.3 1977.01   242.6 1974.85
   252.7 1961.03   272.9 1957.02   293.1 1938.15   404.3 1888.72     707 1788.22
   736.7 1771.18   825.6 1767.23   857.7 1754.02   865.2 1751.73   867.7 1752.03
   954.2 1777.83  1054.2 1829.32  1195.4 1881.78  1286.1 1943.69  1376.9 1984.47
    1518 2025.32  1538.2 2042.05  1669.3 2069.45  1739.9 2090.53    1750 2100.11
#Mann= 3 , 0 , 0
       0     .08       0   857.7    .045       0   867.7     .08       0
Bank Sta=857.7,867.7
XS Rating Curve= 0 ,0
Exp/Cntr=0.3,0.1

Type RM Length L Ch R = 1 ,4266.1  ,391.6,390.6,389.6
XS GIS Cut Line= 4
     1779470.428       78052.764     1779202.181       77558.111
     1778927.214       77265.799     1778304.835       76796.095
#Sta/Elev= 30
      10 2024.08    70.3 2004.05   160.8 1990.96   251.2 1946.85   271.3 1945.33
   341.6  1915.2   482.3 1840.76   502.4 1839.88   552.7 1808.76     643  1773.3
   703.2 1756.83  827.94 1743.75   833.6 1743.34  840.92 1743.51   883.8 1761.62
     954 1767.31     994 1779.16    1014 1795.39    1104 1830.47  1253.9 1915.61
  1333.9 1951.73  1353.9 1972.99  1443.9 2007.25  1463.8 2030.39  1503.8 2052.43
  1523.8 2072.85  1583.8 2081.84  1663.8 2077.44  1693.8 2128.51  1743.7 2126.68
#Mann= 3 , 0 , 0
      10     .08       0  827.94    .045       0  840.92     .08       0
Bank Sta=827.94,840.92
XS Rating Curve= 0 ,0
Exp/Cntr=0.3,0.1

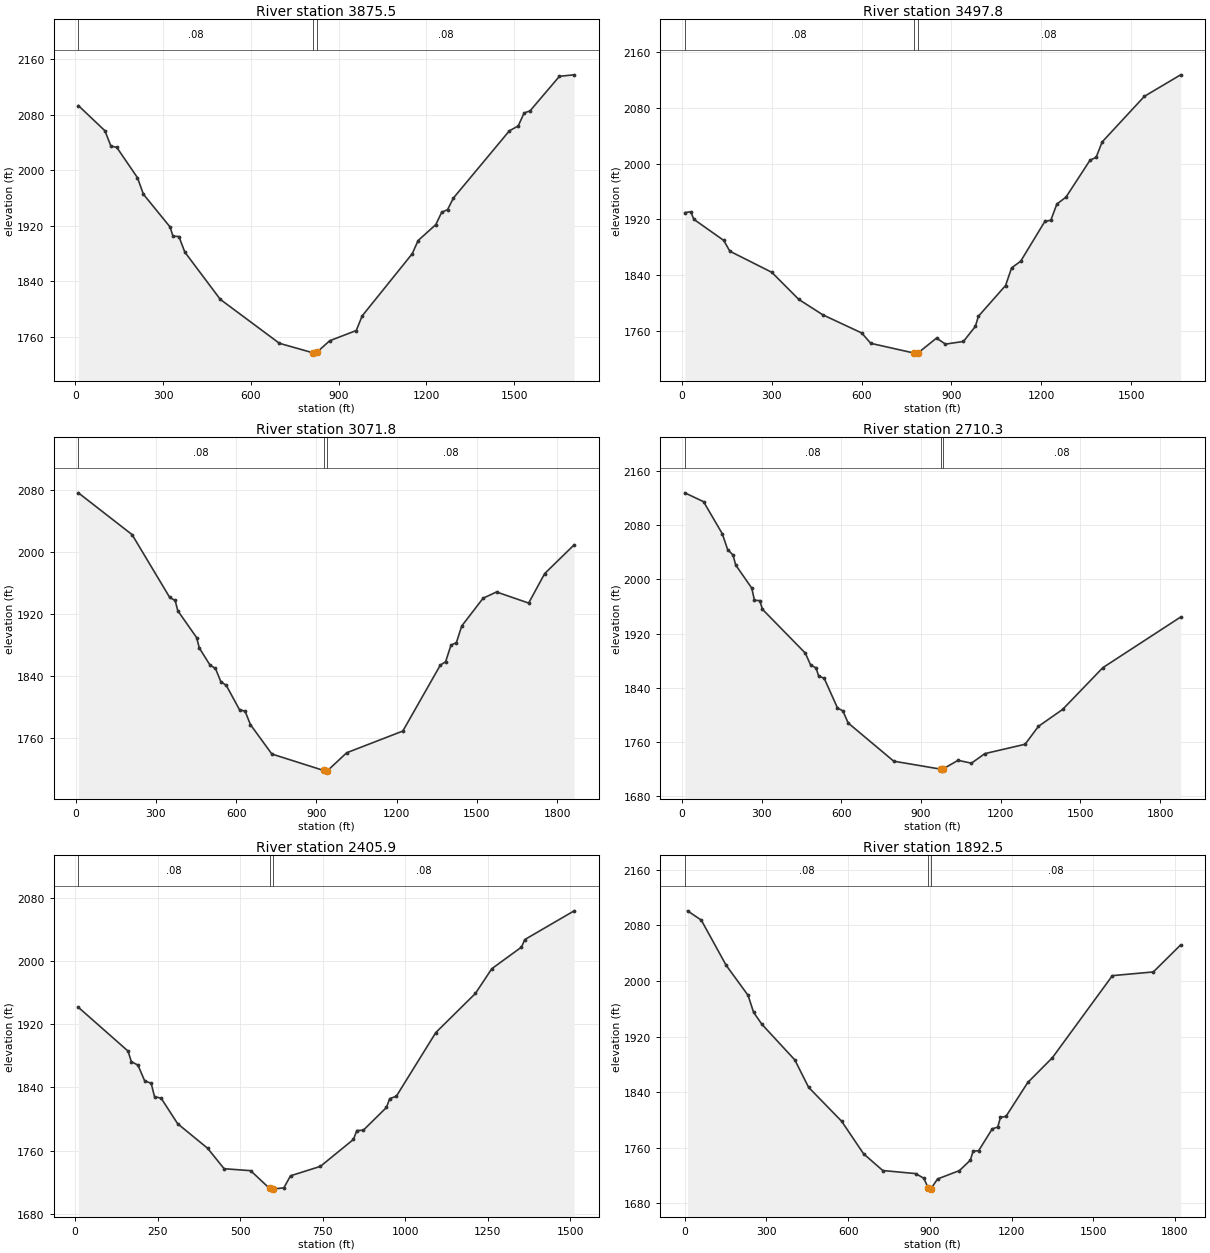
Type RM Length L Ch R = 1 ,3875.5  ,374.3,377.7,381.2
XS GIS Cut Line= 4
     1779686.321       77746.335     1779558.124        77352.07
     1779136.142       76945.442     1778660.093       76426.067
#Sta/Elev= 30
    10.1 2093.11   101.1 2056.74   121.3 2034.83   141.6 2032.78   212.3 1989.11
   232.6 1965.29   323.6 1918.18   333.7 1904.88   353.9 1904.37   374.1 1881.96
   495.4 1813.82   697.5 1750.51   813.3 1736.67   818.7 1736.35  826.53 1737.97
   869.3 1754.17   960.2 1768.94   980.4 1789.98  1151.6 1879.62  1171.7 1898.58
  1232.1 1921.55  1252.2 1939.23  1272.4 1943.17  1292.5 1959.93  1483.7 2056.74
  1513.9 2063.72    1534 2082.43  1554.2 2085.42  1654.8 2135.26  1705.1 2137.37
#Mann= 3 , 0 , 0
    10.1     .08       0   813.3    .045       0  826.53     .08       0
Bank Sta=813.3,826.53
XS Rating Curve= 0 ,0
Exp/Cntr=0.3,0.1

Type RM Length L Ch R = 1 ,3497.8  ,424.8,426,427.2
XS GIS Cut Line= 4
     1779957.929       77495.621     1779695.902       77033.968
     1779432.125       76670.352     1778927.214       76207.227
#Sta/Elev= 30
      10 1929.74      30 1931.04    40.1 1920.16   140.2 1889.72   160.3 1874.28
   300.5 1843.91   390.6 1804.93   470.7 1782.81   600.7 1756.68   630.7 1741.81
  774.21  1727.9   780.4 1727.71  787.89 1727.75   850.3  1749.3   880.2 1740.69
   940.1  1744.5     980 1766.18   990.1  1780.7  1080.8 1824.92    1101 1850.33
  1131.2 1859.82  1211.8    1917  1231.9  1918.8  1252.1 1942.16  1282.3  1951.9
  1362.9 2005.21  1383.1 2009.21  1403.2 2031.36  1544.3 2096.99  1665.2 2127.88
#Mann= 3 , 0 , 0
      10     .08       0  774.21    .045       0  787.89     .08       0
Bank Sta=774.21,787.89
XS Rating Curve= 0 ,0
Exp/Cntr=0.3,0.1

Type RM Length L Ch R = 1 ,3071.8  ,355.4,361.4,367.2
XS GIS Cut Line= 4
     1780321.514       77395.266     1780006.679       76788.745
     1779755.964       76391.781     1779256.367       75886.597
#Sta/Elev= 30
      10 2076.96     211 2022.92   351.7 1941.69   371.8 1937.91   381.9 1924.51
   452.2 1889.83   462.3 1876.36   502.5 1854.19   522.6 1849.98   542.7 1832.82
   562.8 1828.21     613 1796.27   633.1 1794.92   653.2 1777.44   733.3 1739.38
  926.94  1718.1   933.1 1717.24  940.02 1717.39    1013 1740.97  1222.9 1769.04
    1363 1854.19    1383 1858.75  1403.1 1880.24  1423.1 1883.25  1443.1 1904.81
  1523.1 1940.76  1573.2 1948.81  1693.3 1934.47  1753.3 1972.63  1863.4 2009.75
#Mann= 3 , 0 , 0
      10     .08       0  926.94    .045       0  940.02     .08       0
Bank Sta=926.94,940.02
XS Rating Curve= 0 ,0
Exp/Cntr=0.3,0.1

Type RM Length L Ch R = 1 ,2710.3  ,297.6,304.5,311.3
XS GIS Cut Line= 4
     1780420.427       77347.251     1780257.393        76764.37
     1780114.625       76217.674     1780084.762        75511.25
#Sta/Elev= 30
    10.1 2127.81    80.7 2114.77   151.3 2067.43   171.5 2044.07   191.7 2036.08
   201.8 2021.32   262.3 1987.23   272.4  1969.3   292.5 1968.77   302.6 1955.95
     464  1891.3   484.2 1873.52   504.4 1869.58   514.5 1856.94   534.6 1854.53
   585.1 1810.45   605.3 1806.07   625.4 1788.21     797 1731.87  973.91 1720.11
   978.6  1717.2  984.01 1720.71  1039.1 1733.15  1089.6 1728.93    1140 1743.03
  1291.5 1756.83    1342 1783.33  1432.9 1808.23  1584.4 1869.85  1877.3 1944.55
#Mann= 3 , 0 , 0
    10.1     .08       0  973.91    .045       0  984.01     .08       0
Bank Sta=973.91,984.01
XS Rating Curve= 0 ,0
Exp/Cntr=0.3,0.1

Type RM Length L Ch R = 1 ,2405.9  ,515.1,513.3,511.5
XS GIS Cut Line= 4
      1780365.34       77018.567     1780445.429       76635.531
     1780481.922       76224.797     1780549.091       75519.514
#Sta/Elev= 30
      10 1941.56   160.5 1886.12   170.6 1872.74   190.6 1868.33   210.7 1848.69
   230.8 1845.18   240.8 1828.36   260.9 1826.45     311 1794.09   401.4 1763.18
   451.7 1737.18   532.1  1734.7  589.42 1712.17   592.5 1711.34  600.01 1711.43
   632.7 1713.01   652.8 1728.21   743.3 1740.15   843.6 1774.31   853.6 1785.53
   873.5 1785.93   943.4 1814.72   953.3 1825.94   973.3 1828.85    1093 1909.57
  1212.8 1958.99  1262.7 1990.39  1352.5  2017.7  1362.5 2027.26  1512.1 2063.64
#Mann= 3 , 0 , 0
      10     .08       0  589.42    .045       0  600.01     .08       0
Bank Sta=589.42,600.01
XS Rating Curve= 0 ,0
Exp/Cntr=0.3,0.1

Type RM Length L Ch R = 1 ,1892.5  ,212.8,219.1,225.4
XS GIS Cut Line= 4
      1780924.32       77363.951     1780967.751       76708.656
     1780968.916       76175.951     1781003.126        75545.55
#Sta/Elev= 30
    10.1  2100.8    60.6 2087.42   151.6 2022.65   232.4 1979.19   252.6 1954.83
   282.9 1937.69   404.1 1886.28   454.7 1846.87   575.9 1798.11   656.7 1751.19
   727.1 1727.18   847.7 1722.79   877.9 1716.05   893.3 1702.44     898 1700.43
   903.3 1700.66   928.1 1715.03  1008.5  1727.1  1048.7 1742.13  1058.8  1755.3
  1078.9 1755.59  1129.1  1787.2  1149.2  1789.7  1159.3 1803.77  1179.4 1805.05
  1259.6  1853.9  1349.8 1889.45  1570.2 2007.57  1720.6 2012.89  1820.8 2051.76
#Mann= 3 , 0 , 0
       0     .08       0   893.3    .045       0   903.3     .08       0
Bank Sta=893.3,903.3
XS Rating Curve= 0 ,0
Exp/Cntr=0.3,0.1

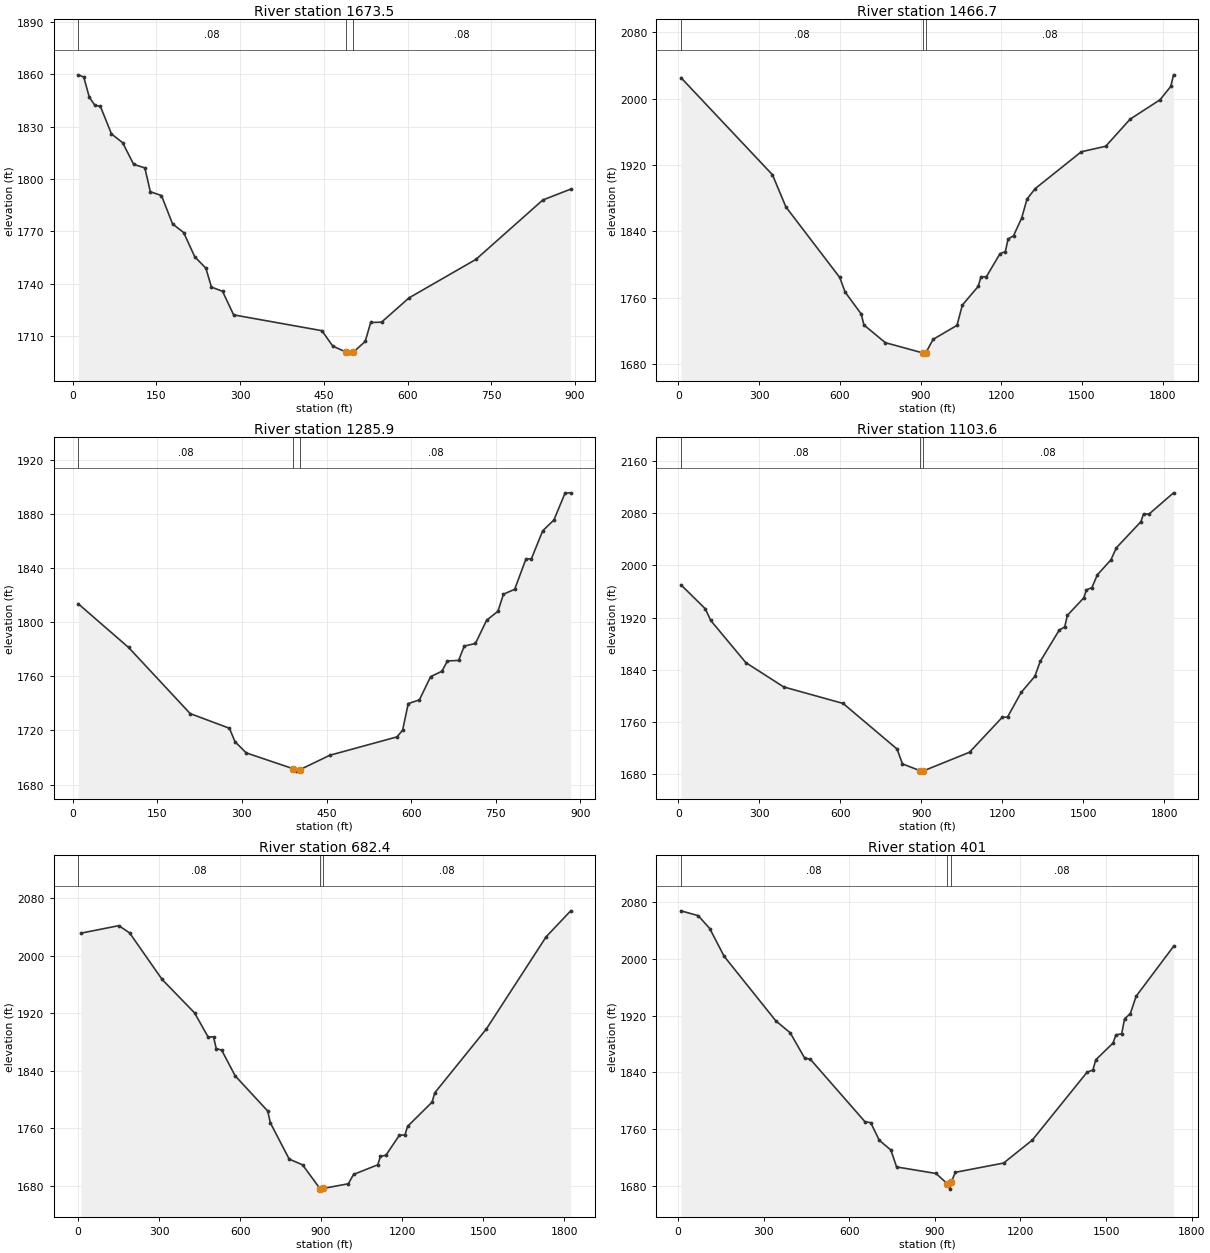
Type RM Length L Ch R = 1 ,1673.5  ,205.6,206.8,207.9
XS GIS Cut Line= 4
     1781029.265       76944.438     1781158.213       76557.594
     1781209.499       76400.805     1781203.638       76081.366
#Sta/Elev= 30
     9.9 1859.62    19.9 1858.38    29.8 1846.88    39.8 1842.19    49.7 1841.63
    69.6 1825.78    89.5 1820.81   109.4 1808.35   129.3 1806.41   139.2 1792.73
   159.1 1790.57     179 1774.33   198.9 1769.39   218.8  1755.5   238.7    1749
   248.6  1738.2   268.5 1735.78   288.4 1722.29   446.6 1713.23     466 1704.41
   490.2 1700.96   495.1  1700.4  502.93 1700.98   524.2 1707.13   533.9 1717.94
   553.3  1718.1   602.7 1732.03   722.5 1754.04   842.3 1788.02   892.2 1794.22
#Mann= 3 , 0 , 0
     9.9     .08       0   490.2    .045       0  502.93     .08       0
Bank Sta=490.2,502.93
XS Rating Curve= 0 ,0
Exp/Cntr=0.3,0.1

Type RM Length L Ch R = 1 ,1466.7  ,176.9,180.7,184.6
XS GIS Cut Line= 4
      1781047.02        77383.51     1781315.965       76705.174
     1781455.251       76346.513     1781553.938       75627.716
#Sta/Elev= 30
      10 2025.22   349.9 1908.12   399.8 1869.35   599.8 1784.28   619.8 1766.69
   679.7 1740.18   689.7 1727.01   769.2 1705.65   909.1 1693.23  917.19 1693.03
   919.1 1693.07   946.7 1709.63  1035.5 1726.52  1055.3 1750.94  1114.5 1773.59
  1124.5 1785.07  1144.7  1785.2  1195.1 1812.86  1215.2 1815.51  1225.3 1830.59
  1245.5 1834.58  1275.7 1855.84  1295.8 1878.91  1326.1 1891.46  1497.4 1935.87
  1588.1 1942.52  1678.8 1975.21  1789.6  1998.5  1829.9 2014.72    1840 2028.66
#Mann= 3 , 0 , 0
      10     .08       0   909.1    .045       0   919.1     .08       0
Bank Sta=909.1,919.1
XS Rating Curve= 0 ,0
Exp/Cntr=0.3,0.1

Type RM Length L Ch R = 1 ,1285.9  ,193.1,182.4,171.6
XS GIS Cut Line= 4
     1781290.092        76931.25     1781489.375       76696.799
      1781578.76       76554.663      1781625.65       76150.236
#Sta/Elev= 30
     9.9 1813.58    99.3 1781.24   208.4 1732.41   277.9 1721.57   287.9  1711.6
   307.7 1703.38  390.22 1691.75   396.6 1689.89  403.34 1691.07   455.9 1701.62
   574.9 1715.19   584.8 1720.11   594.8 1739.75   614.6 1742.55   634.5 1759.72
   654.4 1763.65   664.3  1771.3   684.1  1771.7   694.1 1782.29   713.9 1784.23
   733.8 1801.44   753.7 1807.95   763.6 1820.65   783.4 1824.21   803.3 1846.48
   813.2 1846.91   833.1 1867.46     853 1875.48   872.8  1895.4   882.7 1895.52
#Mann= 3 , 0 , 0
     9.9     .08       0  390.22    .045       0  403.34     .08       0
Bank Sta=390.22,403.34
XS Rating Curve= 0 ,0
Exp/Cntr=0.3,0.1

Type RM Length L Ch R = 1 ,1103.6  ,421.1,421.2,421.3
XS GIS Cut Line= 4
     1781691.602       77562.963     1781702.483       76802.674
      1781712.93       76464.906     1781900.529       75753.978
#Sta/Elev= 30
      10  1970.3     100 1933.55   120.1 1915.65   250.1 1850.93   390.2 1813.67
   610.3 1788.31   810.1 1718.34   829.9 1695.63   895.8 1685.01  899.57 1684.48
   905.8 1684.54  1078.4 1713.49    1199 1766.87  1219.2 1767.64  1269.5 1805.23
  1319.9  1829.8    1340 1852.76  1410.5 1900.94  1430.7 1905.68  1440.7 1923.53
  1501.2 1950.28  1511.3 1962.63  1531.4 1966.03  1551.5 1985.61  1601.9 2008.72
    1622 2027.19  1712.7 2067.12  1722.8 2079.28  1742.9 2078.82  1833.6 2111.48
#Mann= 3 , 0 , 0
      10     .08       0   895.8    .045       0   905.8     .08       0
Bank Sta=895.8,905.8
XS Rating Curve= 0 ,0
Exp/Cntr=0.3,0.1

Type RM Length L Ch R = 1 ,682.4   ,297.6,281.4,264.6
XS GIS Cut Line= 4
     1782074.353       77586.055     1782120.341       76865.353
     1782134.269       76457.942     1782086.597       75764.792
#Sta/Elev= 30
      10  2031.7   150.5 2042.16   190.6 2032.03   310.9 1967.31   431.3 1920.66
   481.4 1887.14   501.5 1887.27   511.5 1870.97   531.6 1868.82   581.7 1832.96
   702.1 1784.06   712.1 1767.41   781.8 1717.04   831.5    1709   897.1 1675.22
   901.1 1675.21   907.1 1676.14  1000.6 1682.66  1020.4  1695.7  1109.9  1709.1
  1119.9 1720.99  1139.9 1722.31  1190.2 1750.36  1210.4 1750.58  1220.4 1762.64
  1311.1 1796.38  1321.1  1809.4  1512.5 1898.41    1734 2026.83  1824.6 2062.82
#Mann= 3 , 0 , 0
       0     .08       0   897.1    .045       0   907.1     .08       0
Bank Sta=897.1,907.1
XS Rating Curve= 0 ,0
Exp/Cntr=0.3,0.1

Type RM Length L Ch R = 1 ,401     ,96.8,108,119.7
XS GIS Cut Line= 4
     1782224.805       77530.442     1782469.673       76720.244
     1782343.655         76586.9     1782189.984       75897.316
#Sta/Elev= 30
    10.1 2067.65    70.5 2060.84   110.8 2042.71   161.2  2003.6   342.6 1912.44
     393 1895.63   443.3 1860.13   463.5 1858.32   654.9 1770.26   675.1 1768.88
   705.3 1743.98   745.6  1730.4   765.8 1706.49   904.3 1697.23     943 1682.95
   952.6 1675.19  956.45 1684.58   971.9 1698.91  1140.9 1711.96  1241.8 1744.53
  1433.6 1840.17  1453.8 1843.08  1463.9 1857.59  1524.4 1881.15  1534.5 1892.76
  1554.7 1894.19  1564.8 1915.37    1585  1922.6  1605.2  1947.1  1736.4 2017.48
#Mann= 3 , 0 , 0
    10.1     .08       0     943    .045       0  956.45     .08       0
Bank Sta=943,956.45
XS Rating Curve= 0 ,0
Exp/Cntr=0.3,0.1

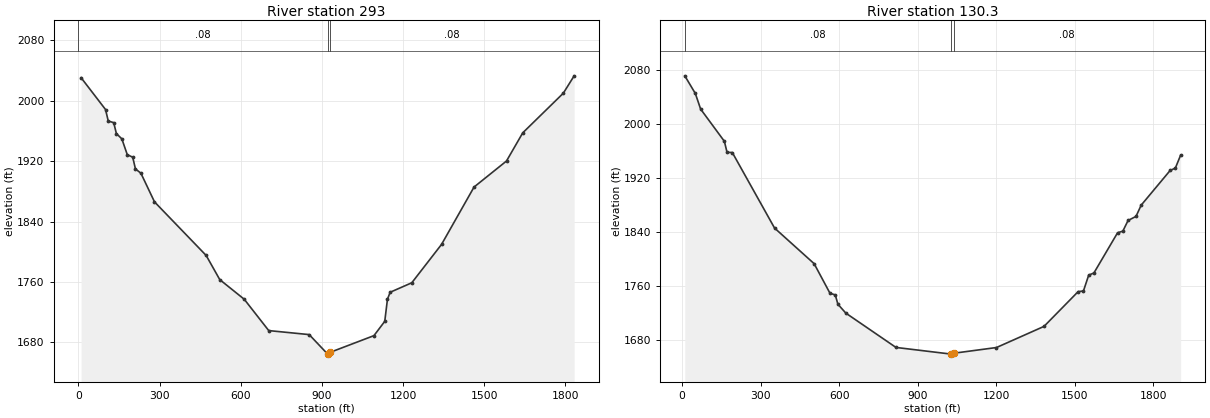
Type RM Length L Ch R = 1 ,293     ,158,162.7,167.5
XS GIS Cut Line= 4
     1782405.877       77516.514     1782547.334       76827.212
      1782475.52       76485.799     1782254.356       75737.897
#Sta/Elev= 30
    10.1 2030.66   100.5 1988.46   110.6 1973.21   130.7 1971.05   140.7 1956.53
   160.8 1949.58   180.9 1928.63     201 1925.25   211.1 1909.71   231.2 1904.08
   281.5 1866.06   472.5 1795.03   522.7 1763.05   613.2 1737.01   703.7  1695.5
   853.2 1690.19   921.5 1664.36     923 1664.31   931.5  1666.8  1092.5  1688.8
  1132.5 1707.74  1142.5 1737.18  1152.5  1746.3  1232.5 1758.88  1342.5 1809.76
  1462.5  1885.7  1582.5 1920.24  1642.5 1957.55  1792.5  2010.1  1832.5 2033.09
#Mann= 3 , 0 , 0
       0     .08       0   921.5    .045       0   931.5     .08       0
Bank Sta=921.5,931.5
XS Rating Curve= 0 ,0
Exp/Cntr=0.3,0.1

Type RM Length L Ch R = 1 ,130.3   ,124.4,130.3,136.2
XS GIS Cut Line= 4
     1782409.359       77572.228     1782653.109       76781.781
     1782663.555       76266.424     1782360.609       75792.852
#Sta/Elev= 30
    10.1 2071.95    50.4  2045.7    70.6 2022.56   161.4 1974.62   171.5  1958.3
   191.7 1958.01   353.1  1845.8   504.4 1792.87   564.9 1748.94   585.1  1746.5
   595.2 1732.62   625.4 1719.44   817.1 1668.45  1028.4 1658.52 1029.23 1658.51
  1038.4 1659.86  1201.1 1668.31  1382.8 1699.73  1513.3  1751.4  1533.4 1752.26
  1553.5 1775.82  1573.5  1779.1  1663.9 1838.82    1684 1841.21    1704 1857.08
  1734.2 1863.07  1754.2 1879.86  1864.7 1931.34  1884.7 1934.91  1904.8 1954.08
#Mann= 3 , 0 , 0
    10.1     .08       0  1028.4    .045       0  1038.4     .08       0
Bank Sta=1028.4,1038.4
XS Rating Curve= 0 ,0
Exp/Cntr=0.3,0.1

Chan Stop Cuts=-1
Use User Specified Reach Order=0